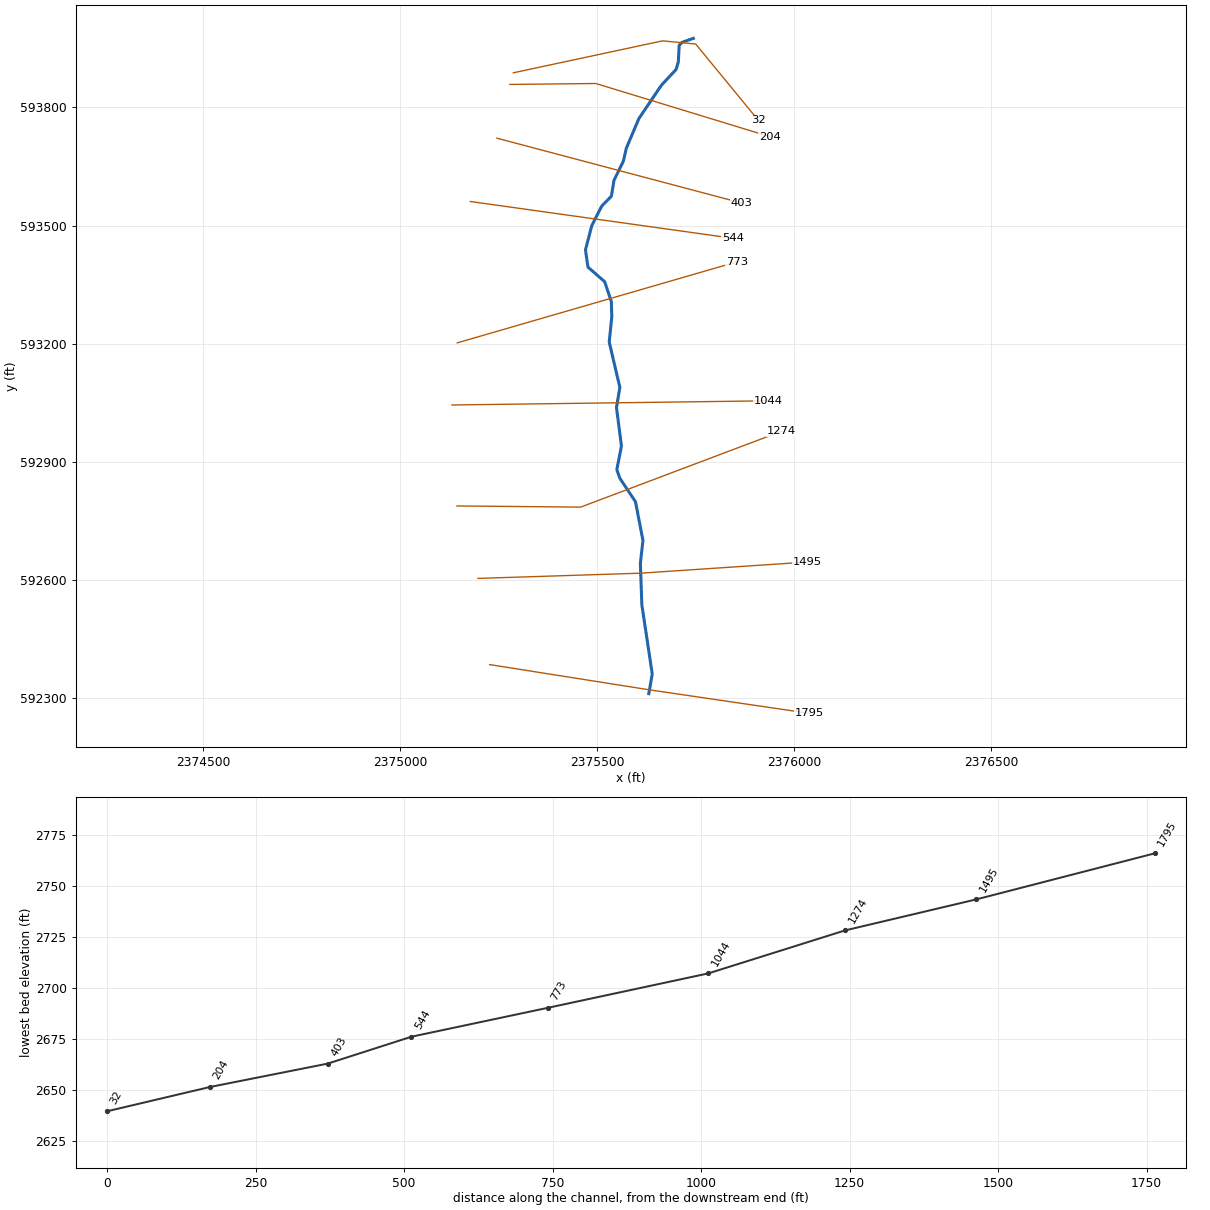
--- HEMLOCKRN.prj (project) ---

Proj Title=HEMLOCKRN
Current Plan=p01
Default Exp/Contr=0,0
English Units
Geom File=g01
Flow File=f01
Plan File=p01
BEGIN DESCRIPTION:
Stream Name: Hemlock Run
Flood Zone: Approximate
Pendleton County, West Virginia
HEC-RAS Version: 5.0.7
Hydrology Method:
Regression equation
END DESCRIPTION:
DSS Export Rating Curves= 0
DSS Export Rating Curve Sorted= 0
DSS Export Volume Flow Curves= 0
DXF OffsetX= 0
DXF OffsetY= 0
DXF ScaleX= 0
DXF ScaleY= 0

--- HEMLOCKRN.p01 (plan) ---

Plan Title=Floodplain
Program Version=5.07
Short Identifier=Floodplain
Geom File=g01
Flow File=f01
Subcritical Flow
K Sum by GR= 0
Std Step Tol= 0.01
Critical Tol= 0.01
Num of Std Step Trials= 20
Max Error Tol= 0.3
Flow Tol Ratio= 0.001
Split Flow NTrial= 30
Split Flow Tol= 0.02
Split Flow Ratio= 0.02
Log Output Level= 0
Friction Slope Method= 1
Unsteady Friction Slope Method= 2
Unsteady Bridges Friction Slope Method= 1
Parabolic Critical Depth
Global Vel Dist= 0 , 0 , 0
Global Log Level= 0
CheckData=True
Encroach Param=-1 ,0,0, 0
Mapping Interval=1HOUR
Computation Time Step Use Courant=        0
Computation Time Step Use Time Series=    0
Computation Time Step Count To Double=0
Computation Time Step Max Doubling=0
Computation Time Step Max Halving=0
Computation Time Step Residence Courant=0
Run HTab= 0
Run UNet= 0
Run Sediment= 0
Run PostProcess= 0
Run WQNet= 0
Run RASMapper= 0
UNET Theta= 0
UNET Theta Warmup= 0
UNET ZTol= 0
UNET ZSATol= 0
UNET MxIter= 0
UNET Max Iter WO Improvement= 0
UNET MaxInSteps= 0
UNET DtIC= 0
UNET DtMin= 0
UNET MaxCRTS= 0
UNET WFStab= 0
UNET SFStab= 0
UNET WFX= 1
UNET SFX= 1
UNET 1D Methodology=Finite Difference
UNET DSS MLevel= 1
UNET Pardiso=0
UNET DZMax Abort= 0
UNET Use Existing IB Tables= 0
UNET Froude Reduction=False
UNET Froude Limit= 0
UNET Froude Power= 0
UNET D1 Cores= 0
UNET D2 Coriolis=0
UNET D2 Cores= 0
UNET D2 Theta= 1
UNET D2 Theta Warmup= 1
UNET D2 Z Tol= 0.01
UNET D2 Volume Tol= 0.01
UNET D2 Max Iterations= 20
UNET D2 Equation= 0
UNET D2 RampUpFraction=0.1
UNET D2 TimeSlices= 1
UNET D2 BCVolumeCheck=0
UNET D1D2 MaxIter= 0
UNET D1D2 ZTol=0.01
UNET D1D2 QTol=0.1
UNET D1D2 MinQTol=1
Write IC File= 0
Write IC File at Fixed DateTime=0
Write IC File at Sim End=0
Echo Input=False
Echo Parameters=False
Echo Output=False
Write Detailed= 0
HDF Write Warmup=0
HDF Write Time Slices=0
HDF Flush=0
HDF Face Node Velocities=0
HDF Compression= 1
HDF Chunk Size= 1
HDF Spatial Parts= 1
HDF Use Max Rows=0
HDF Fixed Rows= 1
Calibration Method= 0
Calibration Iterations= 20
Calibration Max Change=0.05
Calibration Tolerance=0.2
Calibration Maximum=1.5
Calibration Minimum=0.5
Calibration Optimization Method= 1
WQ AD Non Conservative
WQ ULTIMATE=-1
WQ Max Comp Step=1HOUR
WQ Output Interval=15MIN
WQ Output Selected Increments= 0
WQ Output face flow=0
WQ Output face velocity=0
WQ Output face area=0
WQ Output face dispersion=0
WQ Output cell volume=0
WQ Output cell surface area=0
WQ Output cell continuity=0
WQ Output cumulative cell continuity=0
WQ Output face conc=0
WQ Output face dconc_dx=0
WQ Output face courant=0
WQ Output face peclet=0
WQ Output face adv mass=0
WQ Output face disp mass=0
WQ Output cell mass=0
WQ Output cell source sink temp=0
WQ Output nsm pathways=0
WQ Output nsm derived pathways=0
WQ Output MaxMinRange=-1
WQ Daily Max Min Mean=-1
WQ Daily Range=0
WQ Daily Time=0
WQ Create Restart=0
WQ Fixed Restart=0
WQ System Summary=0
WQ Write To DSS=0
WQ Use Fixed Temperature=0
Sorting and Armoring Iterations= 10
XS Update Threshold= 0.02
Bed Roughness Predictor= 0
Hydraulics Update Threshold= 0.02
Energy Slope Method= 1
Volume Change Method= 1
Sediment Retention Method= 0
XS Weighting Method= 0
Number of US Weighted Cross Sections= 1
Number of DS Weighted Cross Sections= 1
Upstream XS Weight=0
Main XS Weight=1
Downstream XS Weight=0
Number of DS XS's Weighted with US Boundary= 1
Upstream Boundary Weight= 1
Weight of XSs Associated with US Boundary= 0
Number of US XS's Weighted with DS Boundary= 1
Downstream Boundary Weight= 0.5
Weight of XSs Associated with DS Boundary= 0.5
Percentile Method= 0
Sediment Output Level= 3
Mass or Volume Output= 0
Output Increment Type= 1
Profile and TS Output Increment= 1
XS Output Flag= 0
XS Output Increment= 10
Write Gradation File= 0
Read Gradation Hotstart= 0
Write HDF5 File= 1
Write Binary Output= 1
Write DSS Sediment File= 0
SV Curve= 0
Specific Gage Flag= 0

--- HEMLOCKRN.f01 (steady flow) ---

Flow Title=Flows
Program Version=5.07
Number of Profiles= 6
Profile Names=P100yr,P10yr,P25yr,P50yr,P500yr,P101yr
River Rch & RM=HEMLOCKRN,Main            ,1795
     534     250     353     441     782     650
River Rch & RM=HEMLOCKRN,Main            ,1495
     596     279     394     492     873     725
Boundary for River Rch & Prof#=HEMLOCKRN,Main            , 1
Up Type= 0
Dn Type= 3
Dn Slope=0.07248
Boundary for River Rch & Prof#=HEMLOCKRN,Main            , 2
Up Type= 0
Dn Type= 3
Dn Slope=0.07248
Boundary for River Rch & Prof#=HEMLOCKRN,Main            , 3
Up Type= 0
Dn Type= 3
Dn Slope=0.07248
Boundary for River Rch & Prof#=HEMLOCKRN,Main            , 4
Up Type= 0
Dn Type= 3
Dn Slope=0.07248
Boundary for River Rch & Prof#=HEMLOCKRN,Main            , 5
Up Type= 0
Dn Type= 3
Dn Slope=0.07248
Boundary for River Rch & Prof#=HEMLOCKRN,Main            , 6
Up Type= 0
Dn Type= 3
Dn Slope=0.07248
DSS Import GetInterval= 0
DSS Import GetPeak= 0
DSS Import FillOption= 0

--- HEMLOCKRN.g01 (geometry) ---

Geom Title=Geometry
Program Version=5.07

River Reach=HEMLOCKRN       ,Main
Reach XY= 30
     2375631.049      592311.441      2375639.75       592361.34
     2375613.348      592537.384     2375609.632      592642.378
     2375616.179      592700.562     2375597.166      592798.806
     2375557.628      592858.111     2375549.829       592880.08
     2375561.542       592940.44     2375548.951      593037.945
     2375557.543       593089.09     2375530.491      593204.311
     2375537.078      593267.966      2375535.94      593306.838
     2375518.937      593357.396     2375476.507       593394.51
     2375470.208      593438.288     2375486.435      593500.231
     2375511.668      593549.653      2375536.03      593574.478
      2375542.84      593615.513      2375566.17      593662.597
     2375574.036      593696.402     2375605.759      593771.478
     2375662.929      593856.108     2375700.235      593896.179
     2375705.922      593914.9782375708.14296168593957.664889115
2375714.92596168593964.793889115     2375744.075      593975.261

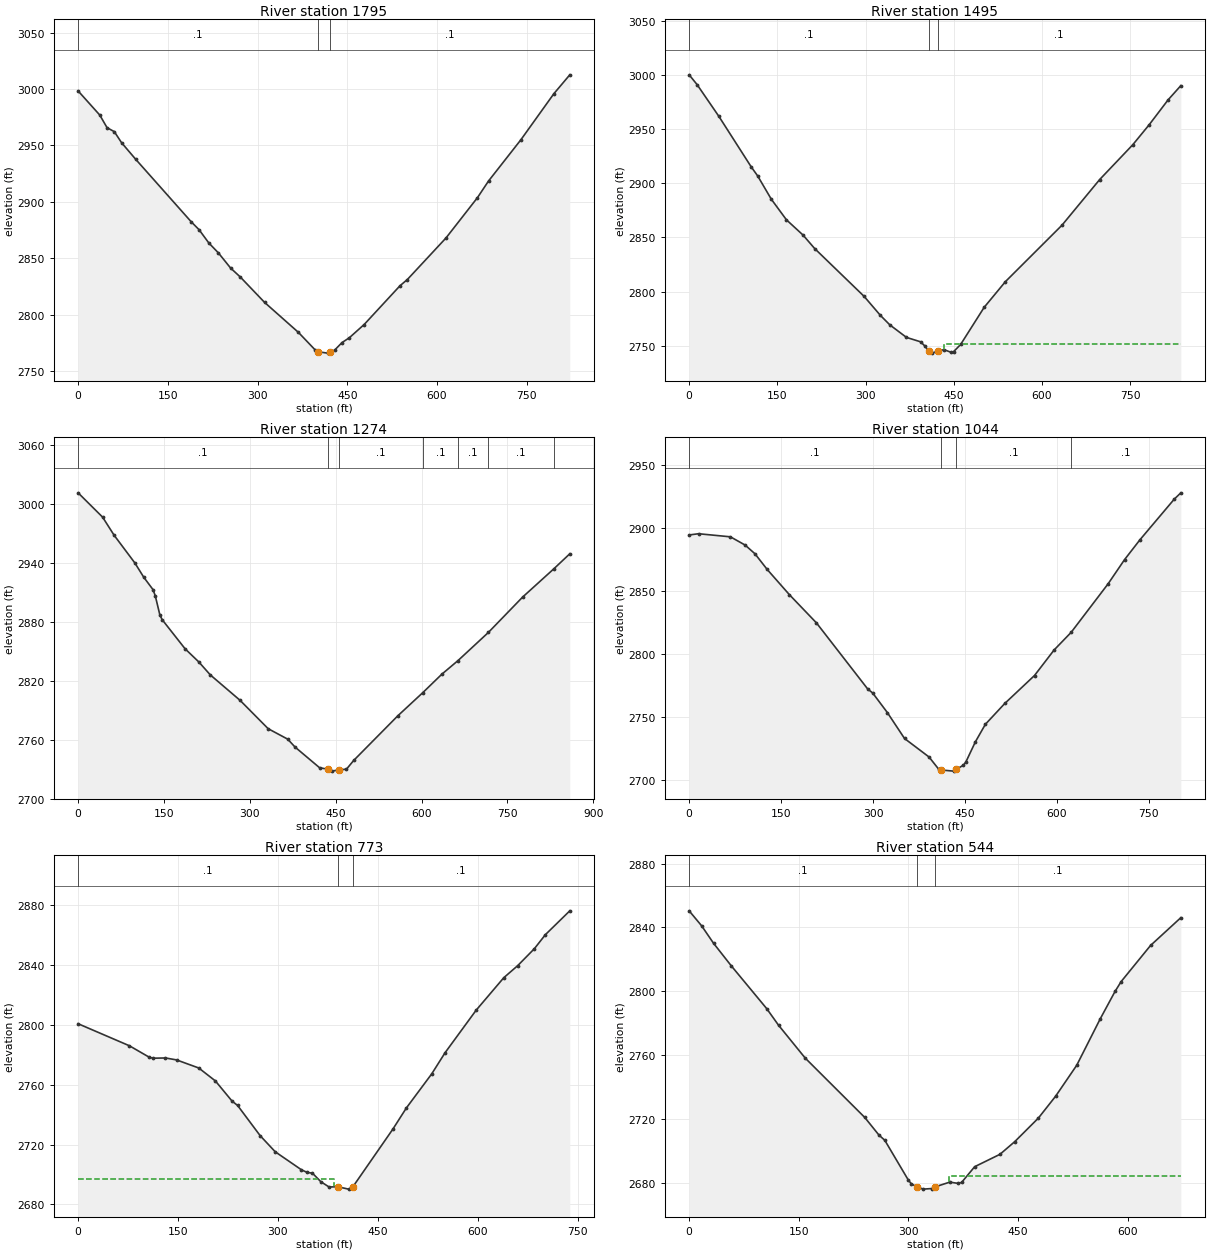
Type RM Length L Ch R = 1 ,1795    ,300,300,300
XS GIS Cut Line= 3
2375226.97345183592385.320454079     2375633.663      592321.064
     2376039.475      592261.472
#Sta/Elev= 30
       0 2998.35    36.2 2976.94    48.4 2965.72    60.5 2962.23    72.7 2952.38
    96.3 2937.68   189.2 2882.19   202.2 2875.25   218.4 2863.55   234.6 2854.61
   254.9 2841.24   271.1 2833.31   311.6 2810.83   368.3 2784.16   396.6 2768.42
   400.7 2767.03   416.9 2765.78   421.7 2766.69     429 2768.57   441.1 2775.12
   453.3 2779.39   478.1 2791.14     538 2825.52   550.3 2831.04     615 2867.97
   667.5 2903.66     686 2918.41   740.3 2955.16   795.3 2995.92   821.9 3012.64
#Mann= 3 ,-1 , 0
       0      .1       0   400.7    .045       0   421.7      .1       0
Bank Sta=400.7,421.7
XS Rating Curve= 0 ,0
Exp/Cntr=0.3,0.1

Type RM Length L Ch R = 1 ,1495    ,221.3,221.3,221.3
XS GIS Cut Line= 3
2375197.36306423592604.104775209     2375610.583       592617.43
2376032.42687155 592645.63122704
#Sta/Elev= 30
       0 3000.01    13.4 2991.06    50.6 2961.65   105.4 2915.21   116.5 2906.77
   139.7 2885.28   165.5 2866.23   193.5 2852.28   213.5 2839.74   297.5 2795.67
   325.2 2778.12   341.3 2769.34   369.6 2757.78   393.6 2753.72   401.6 2749.45
   407.3 2745.09   413.6 2743.28   422.5 2745.26   433.6 2746.45   445.7    2744
   449.7 2744.62   461.7 2751.26   501.8 2785.58   537.9 2809.25   634.1 2861.31
   698.2 2903.42   754.4 2935.47   782.4 2953.98   814.5 2976.89   836.2 2990.04
#Mann= 3 ,-1 , 0
       0      .1       0   407.3    .045       0   422.5      .1       0
#XS Ineff= 2 , 0
                          434.09         2751.68
Permanent Ineff=
       F       F
Bank Sta=407.3,422.5
XS Rating Curve= 0 ,0
Exp/Cntr=0.3,0.1

Type RM Length L Ch R = 1 ,1274    ,230.1,230.1,230.1
XS GIS Cut Line= 3
2375143.90403211 592788.078830442375458.09667212592785.142896914
     2375967.791      592977.483
#Sta/Elev= 30
       0 3010.89    42.8 2986.16    62.8 2967.86    99.1 2939.65   114.8 2924.99
   130.8 2912.55   134.8 2906.24   142.8 2886.82   146.8 2882.02   186.8 2852.44
   210.9    2839   230.9 2825.88   282.9 2800.03     332  2771.2   366.2 2760.55
     379 2752.52   421.8 2731.54   435.9 2730.03   443.2 2728.07     456 2729.37
   468.8 2730.04   481.6 2739.02   558.6 2784.33  602.312807.898   635.5  2826.6
  663.732840.425  716.862869.066   776.6 2904.95  831.412933.829     859 2948.94
#Mann= 7 ,-1 , 0
       0      .1       0   435.9    .045       0     456      .1       0
  602.31      .1       0  663.73      .1       0  716.86      .1       0
  831.41      .1       0
Bank Sta=435.9,456
XS Rating Curve= 0 ,0
Exp/Cntr=0.3,0.1

Type RM Length L Ch R = 1 ,1044    ,270.4,270.4,270.4
XS GIS Cut Line= 2
2375131.49564258593044.4311975442375933.41342841593055.035069092
#Sta/Elev= 30
       0 2894.57    15.3 2895.55    67.3 2893.09    91.3 2886.55   107.3 2879.65
   127.3 2867.18   163.3 2847.26   207.6 2824.77   291.3 2772.23   299.3 2769.12
   323.3 2753.54   351.3 2732.96   391.3 2718.25   407.3  2708.4   411.3 2707.94
   431.3 2707.04   435.3 2708.35   447.3 2711.74   451.3 2714.25     467 2730.42
   483.2 2744.24   514.9  2760.8   563.3 2782.97   595.3 2803.25   623.12817.247
   683.3 2855.73   710.2 2874.99   735.3 2890.75   791.3 2923.03801.9879 2928.03
#Mann= 4 ,-1 , 0
       0      .1       0   411.3    .045       0   435.3      .1       0
   623.1      .1       0
Bank Sta=411.3,435.3
XS Rating Curve= 0 ,0
Exp/Cntr(USF)=0,0
Exp/Cntr=0.3,0.1

Type RM Length L Ch R = 1 ,773     ,229.4,229.4,229.4
XS GIS Cut Line= 2
2375144.75048202593202.163786821 2375853.8843918593407.613798066
#Sta/Elev= 30
       0 2800.85      77 2786.11   106.2  2778.6     112 2777.79   131.2 2777.95
   147.8 2776.65   181.1 2771.25   206.1 2762.59   231.1 2749.11   239.5 2746.15
   273.4 2725.92     296 2715.16   335.2 2703.16   343.6 2701.41   351.9 2700.84
   364.4 2695.17   376.9 2691.59   389.7  2691.8     406 2690.18   412.3 2691.56
   472.7 2730.39     493 2744.56     531 2767.33   551.1 2781.52   597.6 2809.87
   639.2 2831.67   660.1 2839.74   685.1 2851.07   701.7 2860.48   738.3 2876.41
#Mann= 3 ,-1 , 0
       0      .1       0   389.7    .045       0   412.3      .1       0
#XS Ineff= 2 , 0
          384.11 2696.86
Permanent Ineff=
       F       F
Bank Sta=389.7,412.3
XS Rating Curve= 0 ,0
Exp/Cntr(USF)=0,0
Exp/Cntr=0.3,0.1

Type RM Length L Ch R = 1 ,544     ,140.9,140.9,140.9
XS GIS Cut Line= 2
  2375177.767173593561.0542285972375843.78194462593467.779432572
#Sta/Elev= 30
       0 2850.36    17.1 2840.95    33.3 2830.08    57.5 2815.97     106 2789.15
   122.2 2778.75   158.7 2758.15   240.2 2720.94   259.5 2709.96   267.6 2706.64
   299.9 2681.63   303.9 2679.37     311 2677.59   320.1 2676.05   332.1 2676.42
   336.8 2677.52   356.4 2680.43   367.7 2679.67   372.6 2680.22   390.5 2690.09
   425.1 2697.85   445.3 2705.77   477.7 2720.57   501.2 2734.22   530.1 2753.62
   562.2 2782.66   582.6 2799.95   590.9 2806.07   631.1 2828.67   672.5 2846.07
#Mann= 3 ,-1 , 0
       0      .1       0     311    .045       0   336.8      .1       0
#XS Ineff= 2 , 0
                          355.51         2684.52
Permanent Ineff=
       F       F
Bank Sta=311,336.8
XS Rating Curve= 0 ,0
Exp/Cntr(USF)=0,0
Exp/Cntr=0.3,0.1

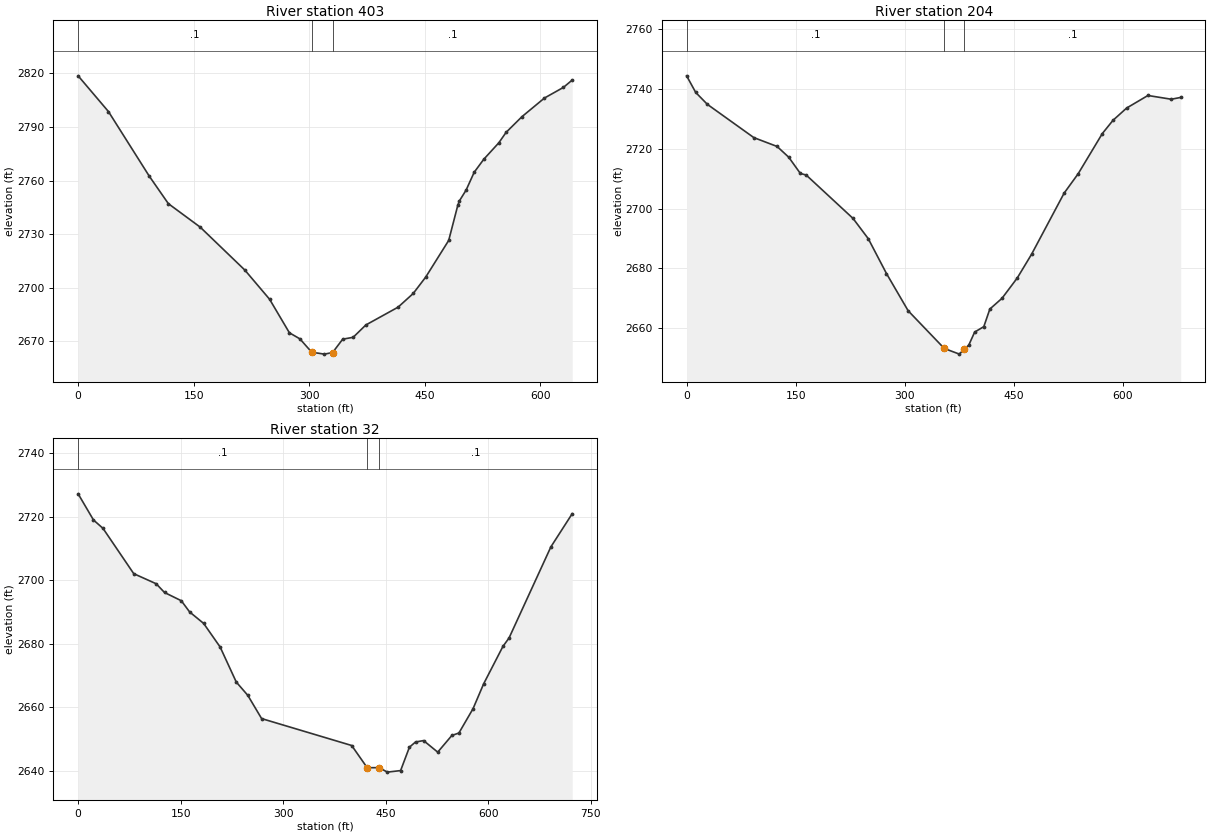
Type RM Length L Ch R = 1 ,403     ,198.7,198.7,198.7
XS GIS Cut Line= 2
2375245.48726172593721.7534926782375865.81374729593557.393483683
#Sta/Elev= 30
       0 2818.55    39.4 2798.56    92.3  2762.5   117.2 2747.05   158.5 2733.94
   216.5 2709.92   248.7 2693.56   274.4 2674.82     288 2671.44   303.4 2663.96
   319.9 2662.89   330.5 2663.78   343.6 2671.24   357.2  2672.3   373.7  2679.2
   415.6 2689.17   435.2 2696.81   451.5 2706.02   481.3 2726.49   493.1 2746.12
   495.3 2748.68   503.9 2754.63   514.4 2764.62   526.9 2771.91   546.4 2781.09
   555.8 2786.91   576.5 2795.73   605.7 2806.14   630.3 2812.08   641.7 2816.19
#Mann= 3 ,-1 , 0
       0      .1       0   303.4    .045       0   330.5      .1       0
Bank Sta=303.4,330.5
XS Rating Curve= 0 ,0
Exp/Cntr(USF)=0,0
Exp/Cntr=0.3,0.1

Type RM Length L Ch R = 1 ,204     ,172.6,172.6,172.6
XS GIS Cut Line= 3
2375278.21660374593858.2188939882375496.52380924593860.604765087
2375937.90996243593725.803048032
#Sta/Elev= 30
       0 2744.28    12.5 2738.74    28.5 2734.77    92.5 2723.66   124.5 2720.71
   140.5 2717.12   156.5  2711.7   164.5 2711.18     229 2696.69   249.9 2689.95
     275  2678.3   304.8 2665.89   354.5 2653.31   375.3 2651.42   381.7 2653.09
   388.1 2654.37   396.3 2658.78   408.9 2660.59   417.2 2666.46   433.9 2670.04
   454.9 2676.82   474.6 2684.74   519.4 2705.14   538.7  2711.6     572 2725.03
   586.7 2729.45   605.4 2733.53   634.7 2737.72   666.8 2736.47   679.8 2737.07
#Mann= 3 ,-1 , 0
       0      .1       0   354.5    .045       0   381.7      .1       0
Bank Sta=354.5,381.7
XS Rating Curve= 0 ,0
Exp/Cntr(USF)=0,0
Exp/Cntr=0.3,0.1

Type RM Length L Ch R = 1 ,32      ,,,
XS GIS Cut Line= 4
2375287.11700012593887.7678225342375666.01043428593968.877603786
2375750.02235494593960.8627867662375909.31876117593766.782346202
#Sta/Elev= 30
       0 2727.17    22.5 2718.93    36.4  2716.3    81.4 2702.04   114.2 2698.87
   126.4 2696.12     151 2693.52   163.2 2689.99   183.7 2686.38   207.8 2678.96
   231.4 2667.94   248.3 2663.74   268.5 2656.43   400.3 2647.96     423 2640.97
   440.5 2640.99   452.5 2639.58   471.9 2640.07   484.8 2647.43   493.7 2649.06
   505.5 2649.51   526.2 2645.87   546.9 2651.12   557.2 2651.89   577.9 2659.55
   593.4 2667.37   621.6 2679.14   630.6 2681.81   691.8 2710.48     723 2720.92
#Mann= 3 ,-1 , 0
       0      .1       0     423    .045       0   440.5      .1       0
Bank Sta=423,440.5
XS Rating Curve= 0 ,0
Exp/Cntr(USF)=0,0
Exp/Cntr=0.3,0.1
LCMann Table=0

Chan Stop Cuts=-1
Use User Specified Reach Order=0
Composite Channel Slope=5